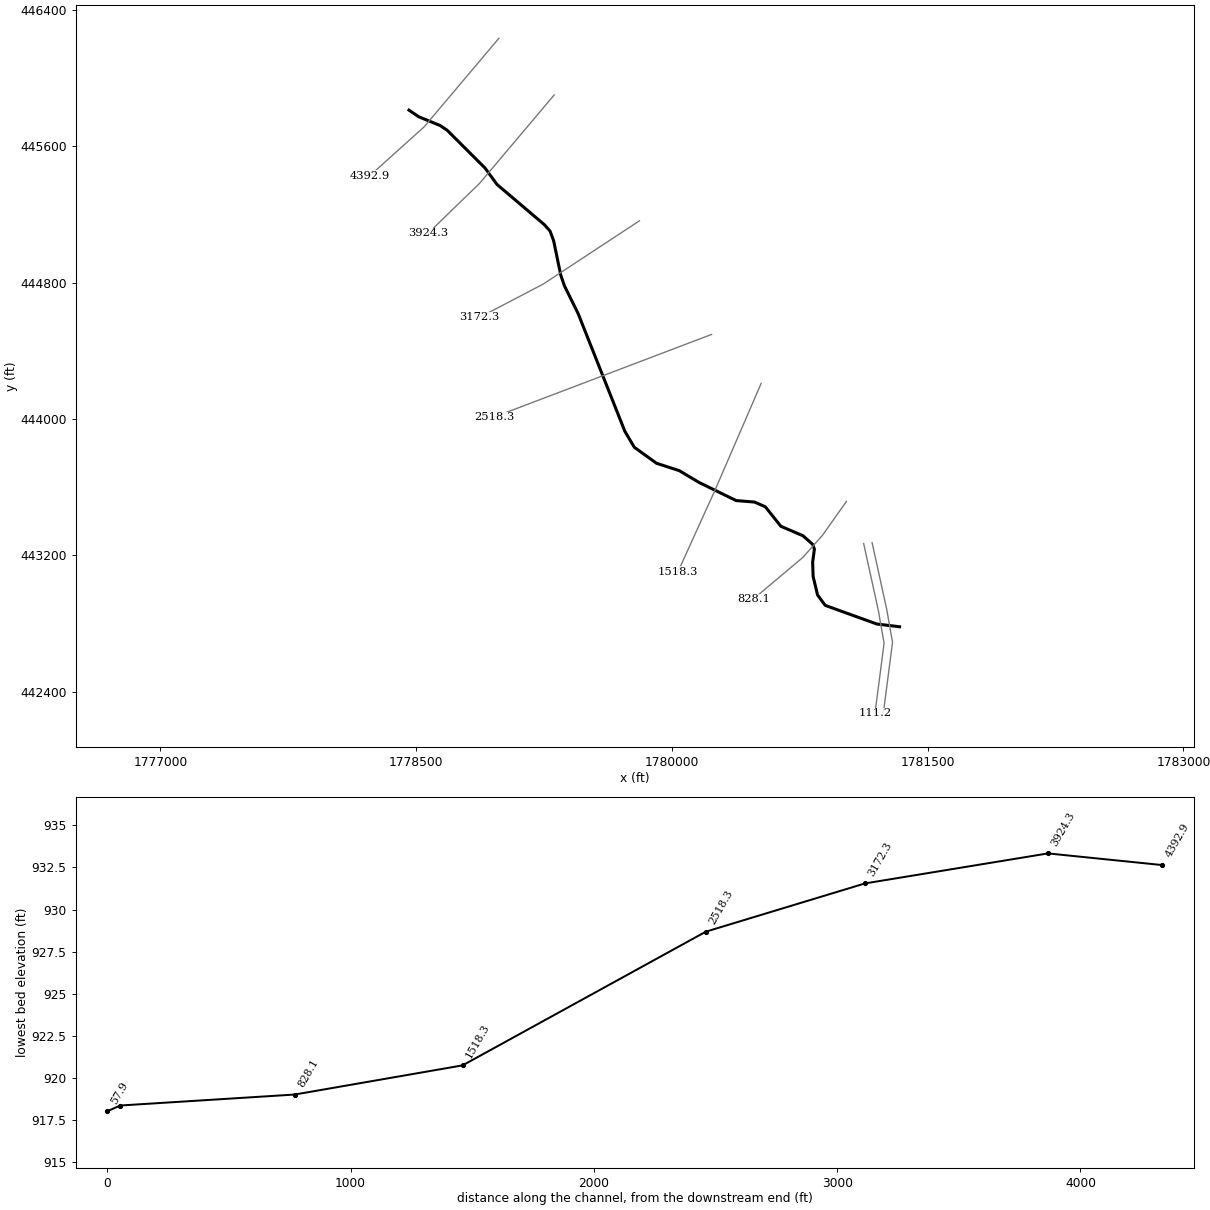
--- RudolphRn.prj (project) ---

Proj Title=RudolphRn
Current Plan=p01
Default Exp/Contr=0,0
English Units
Geom File=g01
Flow File=f01
Plan File=p01
BEGIN DESCRIPTION:
END DESCRIPTION:
DSS Export Rating Curves= 0
DSS Export Rating Curve Sorted= 0
DSS Export Volume Flow Curves= 0
DXF OffsetX= 0
DXF OffsetY= 0
DXF ScaleX= 0
DXF ScaleY= 0

--- RudolphRn.p01 (plan) ---

Plan Title=Floodplain
Program Version=4.00
Geom File=g01
Flow File=f01
K Sum by GR=0
Std Step Tol=0.01
Critical Tol=0.01
Num of Std Step Trials=20
Max Error Tol=0.3
Flow Tol Ratio=0.001
Split Flow NTrial=30
Split Flow Tol=0.02
Split Flow Ratio=0.02
Log Output Level=0
Friction Slope Method=1
Unsteady Friction Slope Method=2
Unsteady Bridges Friction Slope Method=1
Global Log Level=0
CheckData=False
Run HTab=0
Run UNet=0
Run PostProcess=0
UNET Theta=0
UNET Theta Warmup=0
UNET ZTol=0
UNET ZSATol=0
UNET MxIter=0
UNET MaxInSteps=0
UNET DtIC=0
UNET DtMin=0
UNET MaxCRTS=0
UNET WFStab=0
UNET SFStab=0
UNET WFX=0
UNET SFX=0
UNET DSS MLevel=0
UNET DZMax Abort=0
UNET Convert EG Bridges=0
UNET Use Existing IB Tables=0
UNET Froude Limit=0
UNET Froude Power=0
Write IC File=0
Echo Input=False
Echo Output=False
Write Detailed=0

--- RudolphRn.f01 (steady flow) ---

Flow Title=NFF Regression Equation
Program Version=4.10
Number of Profiles= 1
Profile Names=P100yr
River Rch & RM=RudolphRn,Main            ,4392.9
    2582
River Rch & RM=RudolphRn,Main            ,111.2
    2663
Boundary for River Rch & Prof#=RudolphRn,Main            , 1
Up Type= 0
Dn Type= 3
Dn Slope=0.00091
DSS Import GetInterval= 0
DSS Import GetPeak= 0
DSS Import FillOption= 0

--- RudolphRn.g01 (geometry) ---

Geom Title=USGS 10m DEM
Program Version=4.10

River Reach=RudolphRn       ,Main
Reach XY= 30
     1778457.631         445812.     1778514.196      445773.275
     1778639.923      445721.722     1778681.589      445693.944
     1778903.549      445472.348     1778973.901      445375.924
     1779252.346      445139.466     1779285.076      445102.298
     1779305.998       445046.27     1779347.516       444845.35
     1779369.476      444781.263     1779449.595      444618.979
     1779723.901      443928.007     1779779.456      443834.257
     1779909.664      443740.507     1780043.345      443697.104
     1780159.665       443627.66     1780376.679      443521.757
     1780484.318      443513.077     1780547.686      443485.298
     1780638.813      443371.133      1780769.04       443315.16
     1780825.922      443264.288      1780835.51      443236.693
     1780825.332      443160.924     1780828.067      443077.313
     1780854.109      442967.938     1780898.901      442907.065
     1781201.331      442797.799       1781335.2      442781.609

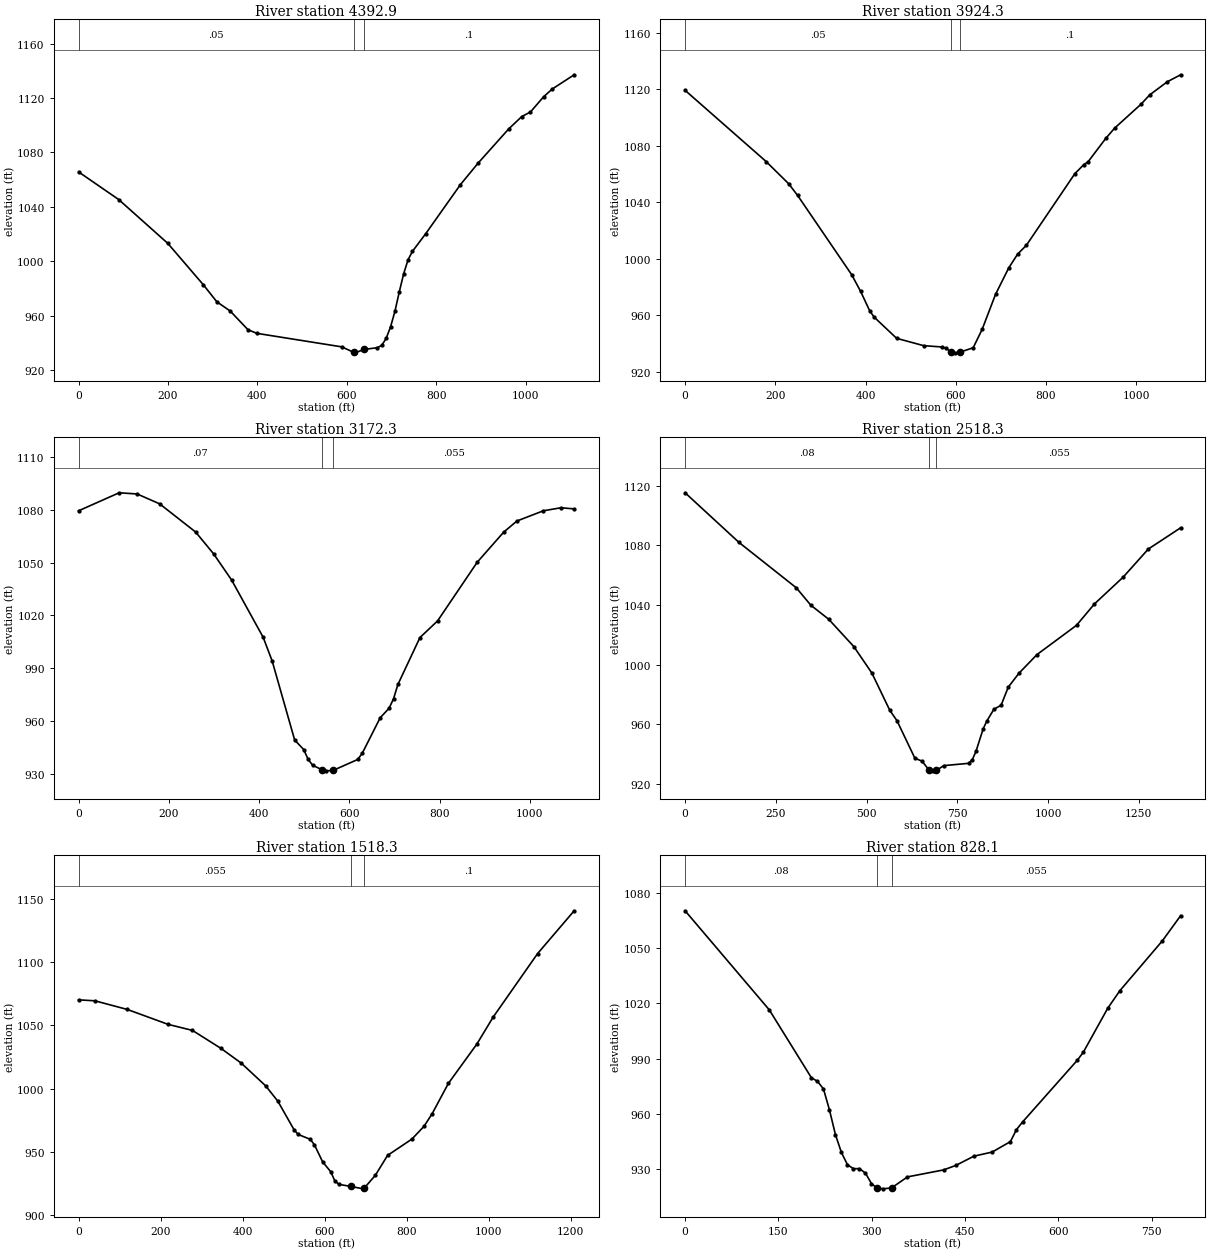
Type RM Length L Ch R = 1 ,4392.9  ,467.8,468.6,468.6
XS GIS Cut Line= 3
      1778984.72      446232.956     1778547.201      445714.413
     1778227.346      445426.402
#Sta/Elev= 30
       0  1065.6    89.8 1045.28   199.6 1013.08   279.4  982.53   309.3  970.16
   339.2  963.36   379.1  949.59   399.1  946.95   588.7  937.04   615.6  933.01
   618.6  932.64   638.6  935.13   668.5  936.42   678.5  938.21   688.2   943.3
     698  951.72   707.8  963.17   717.6  977.54   727.4  990.83   737.2 1001.08
   746.9  1007.2   776.3 1020.04   854.5 1056.34   893.7    1072   962.1 1097.13
   991.5 1106.27  1011.1 1109.67  1040.4 1120.82    1060 1126.59  1108.9 1137.02
#Mann= 3 , 0 , 0
       0     .05       0   615.6    .045       0   638.6      .1       0
Bank Sta=615.6,638.6
XS Rating Curve= 0 ,0
Exp/Cntr=0.3,0.1

Type RM Length L Ch R = 1 ,3924.3  ,758.3,752.1,745.8
XS GIS Cut Line= 3
     1779309.372      445900.925     1778871.854      445382.382
     1778570.228       445090.03
#Sta/Elev= 30
       0  1119.4   179.6 1068.95   229.5 1053.22   249.4 1044.91   369.2  988.74
   389.1  976.89   409.1  963.19     419  958.67   468.9  943.62   528.8  938.42
   568.7   937.5   578.7  936.66   588.7  933.91   598.6  933.33   608.6  933.74
   638.6  936.92   658.5  949.97   688.2  974.81   717.5  993.58   737.1 1003.27
   756.6 1009.59   864.1 1060.38   883.6 1066.65   893.4 1068.79   932.4 1085.28
     952 1092.56  1010.6 1109.54  1030.1 1116.23  1069.2 1125.53  1098.5 1130.43
#Mann= 3 , 0 , 0
       0     .05       0   588.7    .045       0   608.6      .1       0
Bank Sta=588.7,608.6
XS Rating Curve= 0 ,0
Exp/Cntr=0.3,0.1

Type RM Length L Ch R = 1 ,3172.3  ,659.3,654,648.6
XS GIS Cut Line= 3
     1779809.845      445162.986     1779242.913      444790.296
     1778870.595      444595.806
#Sta/Elev= 30
       0 1079.52    89.8 1089.76   129.7 1089.08   179.6 1083.46   259.4 1067.42
   299.3 1054.98   339.2 1040.09   409.1 1007.52     429  994.08   478.9  949.08
   498.9  943.67   508.8  938.09   518.8  934.71   538.8  932.26   548.8  931.55
   563.9  931.77   618.6  938.01   628.6  941.49   668.5  961.75   688.2  967.18
     698   972.5   707.8  980.72   756.6 1007.38   795.7 1016.86   883.6 1050.26
   942.2 1067.35   971.5 1073.69  1030.1 1079.51  1069.2 1081.24  1098.5 1080.59
#Mann= 3 , 0 , 0
       0     .07       0   538.8    .045       0   563.9    .055       0
Bank Sta=538.8,563.9
XS Rating Curve= 0 ,0
Exp/Cntr=0.3,0.1

Type RM Length L Ch R = 1 ,2518.3  ,981.8,1000,1017.5
XS GIS Cut Line= 3
     1780232.547      444496.292     1779594.557      444253.856
     1778956.568      444011.419
#Sta/Elev= 30
       0 1115.19   148.4  1081.9   306.6  1051.4   346.2 1039.81   395.6 1030.36
   464.9 1011.99   514.4  994.31   563.8  969.32   583.6  962.32     633  937.15
   652.8  935.17   672.6  928.99   682.5  928.69   692.4  928.96   712.2  932.18
   781.4  933.73   791.3  936.29   801.2   941.7     821  956.83   830.9  961.99
   850.6     970   870.4  972.67   890.2  984.84   919.9  994.22   969.4 1006.69
  1078.2  1026.3  1127.6 1040.65  1206.7 1058.62    1276 1077.46    1365  1091.7
#Mann= 3 , 0 , 0
       0     .08       0   672.6    .045       0   692.4    .055       0
Bank Sta=672.6,692.4
XS Rating Curve= 0 ,0
Exp/Cntr=0.3,0.1

Type RM Length L Ch R = 1 ,1518.3  ,696.5,690.2,684.7
XS GIS Cut Line= 3
     1780523.082      444208.497      1780251.54      443580.252
     1780034.695      443102.727
#Sta/Elev= 30
       0 1070.03    39.7 1069.27     119 1062.42   218.2 1050.67   277.7 1045.89
   347.2  1031.7   396.8 1020.04   456.3  1002.1     486  989.98   525.7  967.34
   535.6  963.73   565.4  959.82   575.3  955.48   595.2  942.12     615  934.28
   624.9  927.13   634.8  924.31   664.6  922.62   694.3  920.76  696.95  921.39
     724  931.53   753.7  947.17   813.1  960.08   842.7  970.19   862.5  980.14
   902.1 1004.08   971.4 1035.06    1011 1056.28  1119.8 1106.63  1208.9 1140.38
#Mann= 3 , 0 , 0
       0    .055       0   664.6    .045       0  696.95      .1       0
Bank Sta=664.6,696.95
XS Rating Curve= 0 ,0
Exp/Cntr=0.3,0.1

Type RM Length L Ch R = 1 ,828.1   ,697.1,716.9,736
XS GIS Cut Line= 4
     1781023.411      443516.645     1780883.871      443319.307
     1780768.853      443189.099      1780476.97      442943.873
#Sta/Elev= 30
       0  1070.5   135.4  1016.5     203  979.56   212.7  977.62   222.4  973.49
     232   962.1   241.7  948.52   251.3  938.83     261  932.16   270.6  930.02
   280.3  930.02     290  927.56   299.6  921.88   308.4  919.51   318.9  919.03
   332.1  919.59   357.5  925.54   415.4  929.33     435  931.75   464.3  936.83
   493.6  939.06     523  944.76   532.7  951.32   542.5  955.45   630.5  989.08
   640.2  993.48   679.4  1017.4   698.9 1026.96   767.3 1054.16   796.6 1067.83
#Mann= 3 , 0 , 0
       0     .08       0   308.4    .045       0   332.1    .055       0
Bank Sta=308.4,332.1
XS Rating Curve= 0 ,0
Exp/Cntr=0.3,0.1

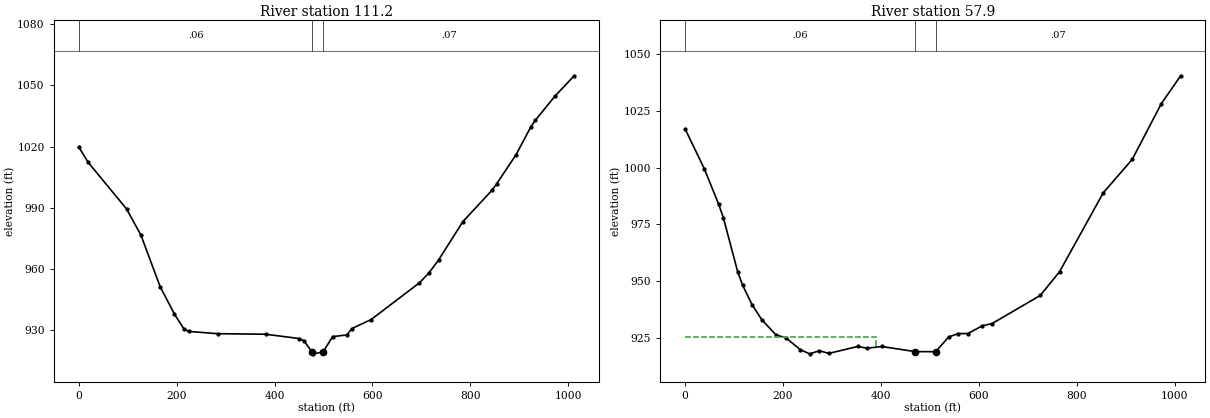
Type RM Length L Ch R = 1 ,111.2   ,53.1,53.3,53
XS GIS Cut Line= 4
     1781124.539      443269.683     1781210.477      442877.756
     1781244.331      442685.048     1781190.945      442273.589
#Sta/Elev= 30
       0 1019.91    19.6 1012.25    97.9  989.44   127.2  976.61   166.4  951.34
   195.7  937.85   215.3  930.44   225.1  929.38   283.8  928.26   381.7     928
   450.2  925.89   459.9  924.85  476.88  919.16   479.5  918.38   499.1  919.29
   518.6  926.83     548  927.66   557.8  930.77   596.9  935.15   695.7  953.18
   715.4  958.08   735.2  964.52   784.6  983.24   843.9  998.58   853.7 1001.82
   893.3 1016.13   922.9 1029.52   932.8 1033.03   972.3 1044.69  1011.8 1054.76
#Mann= 3 , 0 , 0
       0     .06       0  476.88    .045       0   499.1     .07       0
Bank Sta=476.88,499.1
XS Rating Curve= 0 ,0
Exp/Cntr=0.3,0.1

Type RM Length L Ch R = 1 ,57.9    ,62.3,57.9,53.3
XS GIS Cut Line= 4
     1781174.018      443274.891     1781259.956      442882.964
      1781293.81      442690.256     1781240.425      442278.798
#Sta/Elev= 30
       0 1017.01    39.2  999.47    68.5   983.9    78.3  977.84   107.6  953.98
   117.4  948.25     137  939.57   156.6  933.08   185.9  926.28   205.5  925.18
   234.9  919.92   254.4  918.04     274   919.4   293.6  918.24   352.3  921.28
   371.9  920.52   401.2  921.27   469.7  919.02  511.68  918.98   538.2  925.49
   557.8  926.96   577.3  926.96   606.8  930.37   626.5  931.32   725.3  943.74
   764.8  954.25   853.7  988.87     913 1003.62   972.3 1028.09  1011.8 1040.39
#Mann= 3 , 0 , 0
       0     .06       0   469.7    .045       0  511.68     .07       0
#XS Ineff= 2 , 0
          389.73  925.63
Permanent Ineff=
       F       F
Bank Sta=469.7,511.68
XS Rating Curve= 0 ,0
Exp/Cntr=0.3,0.1

Chan Stop Cuts=-1
Use User Specified Reach Order=0
Composite Channel Slope=5